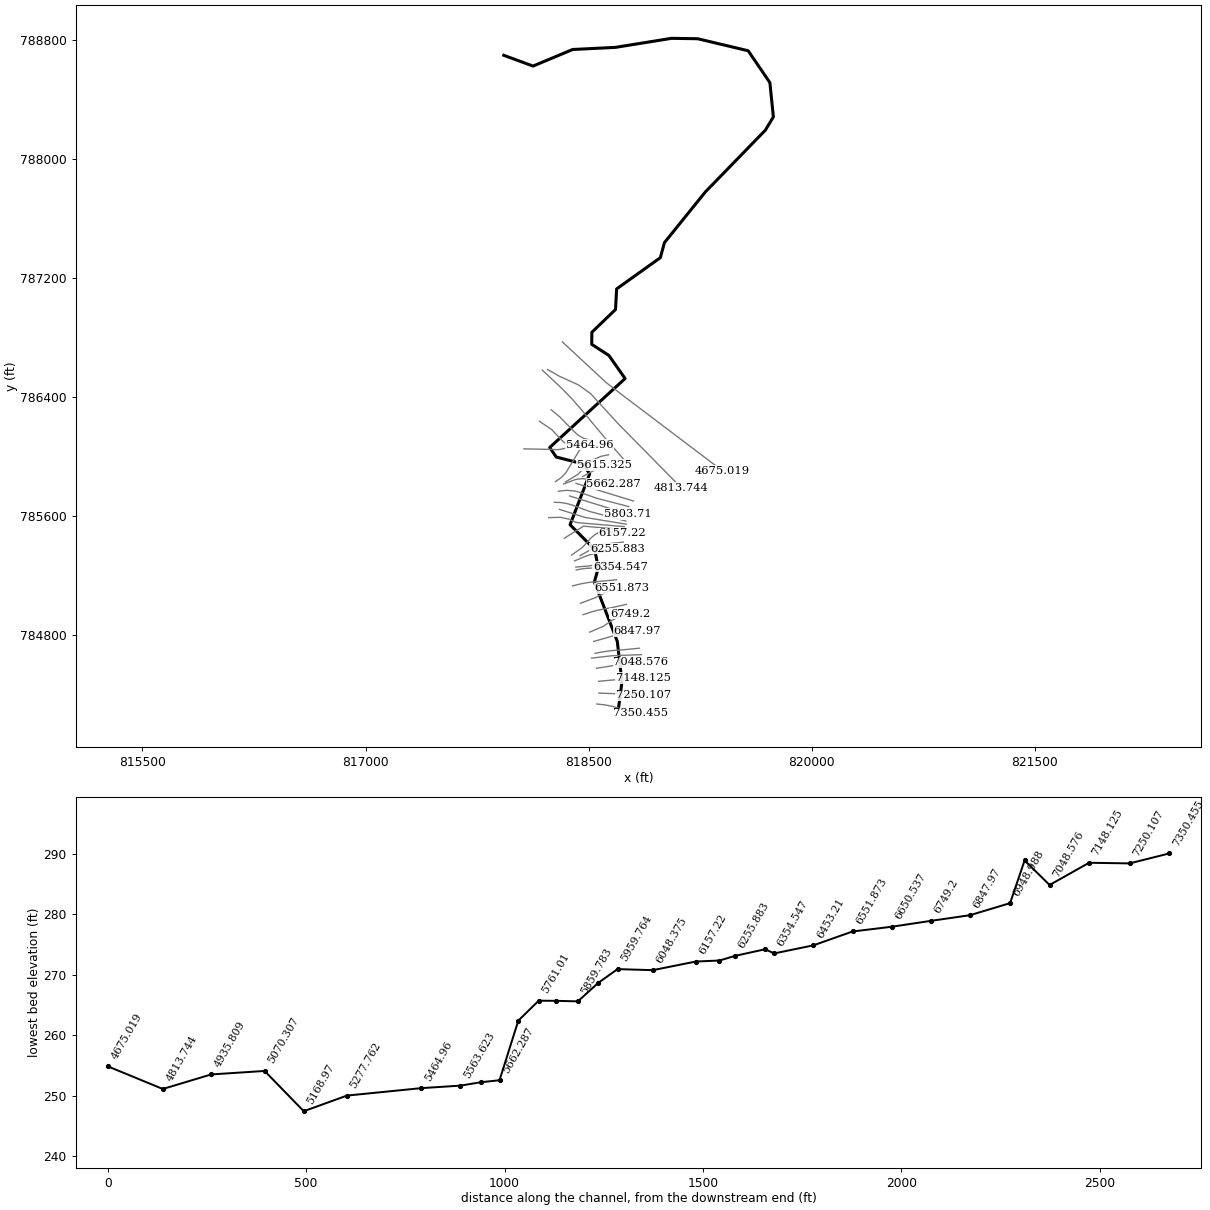
--- 17401_ras.prj (project) ---

Proj Title=17401
Current Plan=p01
Default Exp/Contr=0.3,0.1
English Units
Geom File=g01
Flow File=f01
Plan File=p01
Y Axis Title=Elevation
X Axis Title(PF)=Main Channel Distance
X Axis Title(XS)=Station
BEGIN DESCRIPTION:
RFD model 17401 exported to HEC-RAS
END DESCRIPTION:

--- 17401_ras.p01 (plan) ---

Plan Title=Plan 01
Program Version=4.10
Short Identifier=Plan 01
Geom File=g01
Flow File=f01
Subcritical Flow
Calc Critical at every XS
Secant Critical Depth

--- 17401_ras.f01 (steady flow) ---

Flow Title=Flow 01
Program Version=5.01
Number of Profiles= 6
Profile Names=10yr,25yr,50yr,100yr,100plus,500yr
River Rch & RM=17401,33,7350.455
   139.7  226.71  308.84  385.29  562.53 1019.81
River Rch & RM=17401,33,6048.375
  153.62  249.46  340.01  424.32   619.5 1108.59
River Rch & RM=17401,33, 5910.78
  158.58  257.58  351.12  438.23  639.82 1139.96
River Rch & RM=17401,33, 5803.71
  165.39  268.72   366.4  457.36  667.74 1182.85
River Rch & RM=17401,33,5563.623
  167.27  271.79  370.61  462.63  675.44 1194.66
River Rch & RM=17401,33,5277.762
   168.4  273.63  373.13  465.79  680.06 1201.72
River Rch & RM=17401,33,4935.809
  167.27  271.79  370.61  462.63  675.44 1194.66
Boundary for River Rch & Prof#=17401,33,1
Up Type= 0
Dn Type= 2
Boundary for River Rch & Prof#=17401,33,2
Up Type= 0
Dn Type= 2
Boundary for River Rch & Prof#=17401,33,2
Up Type= 0
Dn Type= 2
Boundary for River Rch & Prof#=17401,33,2
Up Type= 0
Dn Type= 2
Boundary for River Rch & Prof#=17401,33,2
Up Type= 0
Dn Type= 2
Boundary for River Rch & Prof#=17401,33,2
Up Type= 0
Dn Type= 2

--- 17401_ras.g01 (geometry) ---

Geom Title=17401
Program Version=4.10

River Reach=17401,33
Reach XY= 30
818700.436303646784305.637228769818723.792577565784484.607912779
818692.219333112784757.134865001818538.367376359785155.485162502
818564.598666313785250.204636629 818540.41130987785374.303178994
818374.855177254785540.827476155818506.525551765785882.589551206
818461.989983919785949.392902986818281.625216783785996.232174349
818237.991441729786060.206523601818744.915799231786523.768135137
818635.883028747  786678.9350539818520.564946653786753.834059938
818521.386652443786834.882614891818680.253050509786987.556196349
818687.990835219787126.380457851818981.790963681 787336.33542561
819009.271113399787437.295451769819284.839295239787778.811574531
819687.654876561788193.269092558819741.764314683788282.842266064
819718.314129741788513.239136789819572.399965796788727.573271181
819232.296784315788808.428077574819056.435481401788811.065622534
818680.313946518788750.336654273818392.428758385788736.054056175
818125.980701655788624.576845874817929.202714475788696.975309827

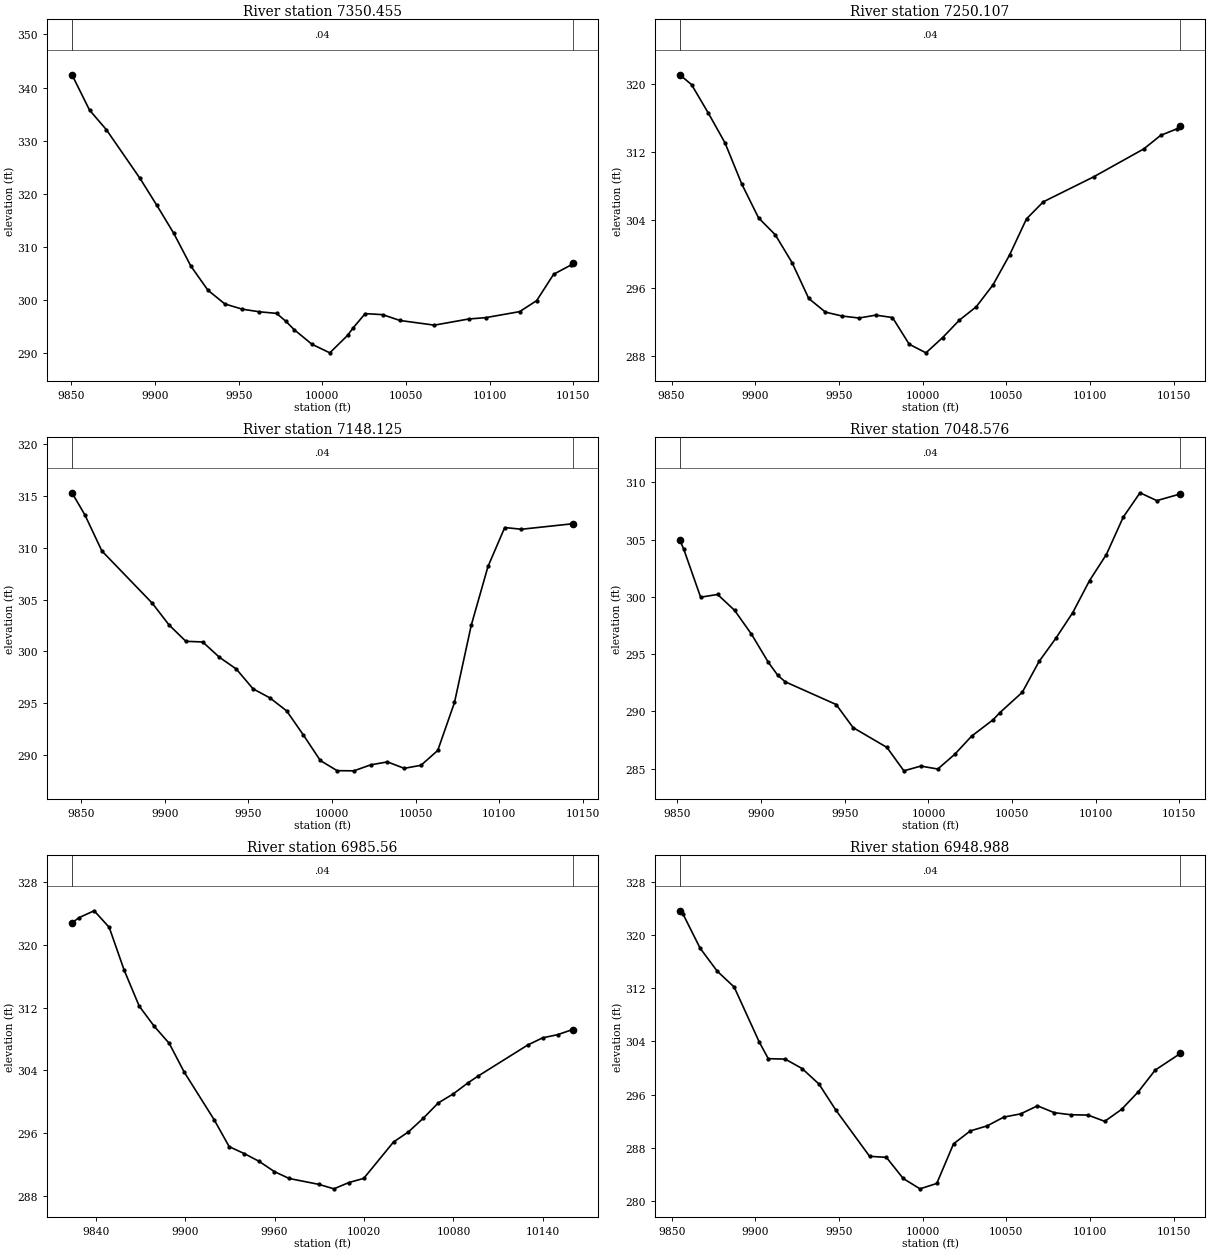
Type RM Length L Ch R = 1 ,7350.455,100.348200,100.348200,100.348200
XS GIS Cut Line= 6
818554.613288098784335.654357114818607.320029541784329.651295234
818648.273603784784322.284886794818680.350882243784313.981655035
818748.477978562 784291.44467328818846.195589676784272.453711538
#Sta/Elev= 29
 9850.42342.40829860.874335.75959870.939332.06689891.068322.87889901.133317.8022
9911.271312.51359921.431306.37169931.592 301.8339941.752299.22779952.027298.2549
9962.356 297.7489972.686297.45289978.213295.96239983.153294.3879 9993.78291.6386
10004.47290.016110015.14293.318310018.18294.625810025.61297.404410036.01297.2148
10046.41296.112410066.94295.233910087.41296.389910097.64296.648910117.93297.7813
10128.08299.850410138.23304.821810148.38306.529410149.59306.8882
#Mann= 3 , 0 , 0
 9850.42    0.04       0 9850.42    0.04       010149.59    0.04       0
#XS Ineff= 2 , 0
       0                               0
Bank Sta=9850.42,10149.59
Exp/Cntr=0.3,0.1

Type RM Length L Ch R = 1 ,7250.107,101.982400,101.982400,101.982400
XS GIS Cut Line= 5
818567.952656993784408.892279011818716.454288749784403.245565427
818718.452776367 784403.16780143818741.306043383784402.147990436
 818866.75918677784393.705203502
#Sta/Elev= 28
9854.866321.10459861.918319.94659871.925316.60089881.933313.0815 9891.94308.2423
9901.947 304.2629911.954 302.2669921.961299.00019931.969294.76469941.976293.1567
9951.983292.6964 9961.99292.46629971.998292.80539982.005292.52489992.012289.3823
10002.02288.366510012.03290.170910022.04292.224910032.05293.783210042.08296.3641
 10052.1 299.92510062.12304.142410072.14306.144810102.21309.082810132.28312.3843
 10142.3313.970910152.32314.762410154.09315.0652
#Mann= 3 , 0 , 0
9854.866    0.04       09854.866    0.04       010154.09    0.04       0
#XS Ineff= 2 , 0
       0                               0
Bank Sta=9854.866,10154.09
Exp/Cntr=0.3,0.1

Type RM Length L Ch R = 1 ,7148.125,99.548400,99.548400,99.548400
XS GIS Cut Line= 5
818567.228590075784488.160497805818715.220946693784501.715784965
 818717.21681255784501.844313103818761.554957952784505.666160099
818865.539716411784510.549644339
#Sta/Elev= 27
9844.605315.32149852.409313.1517 9862.45309.70399892.576304.65859902.618302.5552
 9912.66300.97779922.702300.91639932.743299.43369942.785 298.3049952.827296.3877
9962.869295.51769972.911294.25659982.953291.91659992.995289.470710003.03288.4877
10013.07 288.471 10023.1289.048210033.14289.333710043.17 288.71310053.18289.0064
10063.19290.4374 10073.2295.072810083.21302.523110093.22308.203610103.23311.9647
10113.25311.799810143.82312.3307
#Mann= 3 , 0 , 0
9844.605    0.04       09844.605    0.04       010143.82    0.04       0
#XS Ineff= 2 , 0
       0                               0
Bank Sta=9844.605,10143.82
Exp/Cntr=0.3,0.1

Type RM Length L Ch R = 1 ,7048.576,63.015900,63.015900,63.015900
XS GIS Cut Line= 5
818552.668840603784575.879824454818699.472131148784598.985483002
818701.442361813784599.329272362818741.480535715784605.584609403
818849.002438601784616.490934047
#Sta/Elev= 29
 9851.39 304.9579853.749304.16829863.872299.96469873.996300.20499884.119298.8264
9894.242296.73959904.365294.27439910.048293.13239914.488292.57479944.857290.5972
 9954.98288.58059975.227286.8497 9985.35284.80599995.473285.2228 10005.6284.9631
10015.72286.246510025.84287.835810038.74 289.27310042.52289.861110056.11 291.665
10066.16294.358410076.22  296.3910086.27298.619410096.32301.420310106.37303.6913
10116.42 306.94710126.47309.080910136.52308.3959 10150.6308.9808
#Mann= 3 , 0 , 0
 9851.39    0.04       0 9851.39    0.04       0 10150.6    0.04       0
#XS Ineff= 2 , 0
       0                               0
Bank Sta=9851.39,10150.6
Exp/Cntr=0.3,0.1

Type RM Length L Ch R = 1 , 6985.56,36.572100,36.572100,36.572100
XS GIS Cut Line= 3
818520.228238225784644.135884807818657.322589219784659.922507033
818855.070804507784667.400380716
#Sta/Elev= 30
9824.107322.84329828.911323.51679838.977 324.3849849.043322.27279859.109316.7931
9869.175 312.2089879.241309.62979889.307307.44659899.373303.77439919.505297.6714
9929.571294.23819939.637293.36089949.704292.3563 9959.77291.0651 9969.79290.1749
9989.805  289.429999.812288.851210009.82289.652210019.83290.186110039.84294.8421
10049.85 296.13210059.85 297.88810069.86299.833210079.87300.978410089.88302.4094
10096.48303.2508 10129.9307.233610139.91 308.15110149.92308.5508   10160309.2104
#Mann= 3 , 0 , 0
9824.107    0.04       09824.107    0.04       0   10160    0.04       0
#XS Ineff= 2 , 0
       0                               0
Bank Sta=9824.107,10160
Exp/Cntr=0.3,0.1

Type RM Length L Ch R = 1 ,6948.988,101.018400,101.018400,101.018400
XS GIS Cut Line= 6
818543.041217873784676.093695019  818595.1503996784686.058937487
818645.586604441  784693.4452524818689.998942629784697.196535077
818740.908985968784700.743653147818839.990876719784710.664714354
#Sta/Elev= 30
9854.777323.65939856.771323.14849866.952318.02879877.133314.58049887.315312.1777
9902.193303.96019907.677301.39899917.785301.33069927.892299.91679937.998297.5763
9948.105 293.6449968.251286.70079978.287286.54319988.323283.36689998.358281.8057
10008.39282.614610018.41288.580110028.44290.524210038.46291.279610048.49292.6073
10058.52293.088210068.57294.301910078.62293.268510088.67292.954410098.72292.9091
10108.77291.968210118.82293.761110128.87296.421110138.92299.675910153.99302.1869
#Mann= 3 , 0 , 0
9854.777    0.04       09854.777    0.04       010153.99    0.04       0
#XS Ineff= 2 , 0
       0                               0
Bank Sta=9854.777,10153.99
Exp/Cntr=0.3,0.1

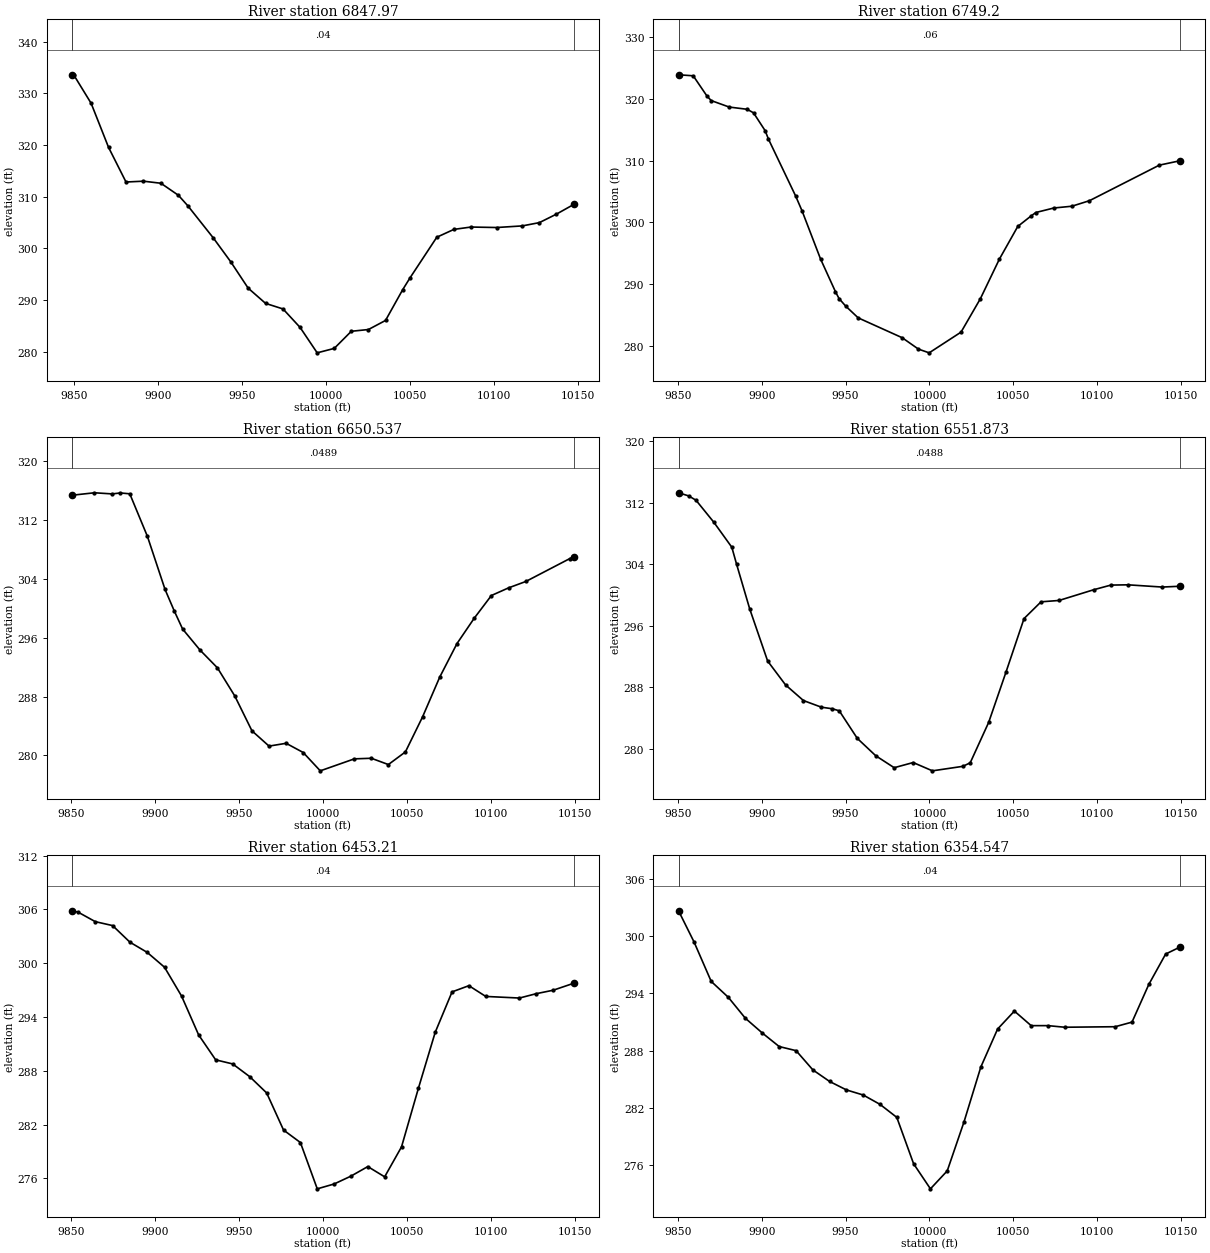
Type RM Length L Ch R = 1 , 6847.97,98.769600,98.769600,98.769600
XS GIS Cut Line= 5
818534.090314223784755.968744566818654.936952971 784790.65309852
 818677.40499146784794.898231659818679.387110957784795.165069252
818825.173990401784823.904204238
#Sta/Elev= 30
9848.606333.53349849.553 333.5689859.956328.0656 9870.36 319.5369880.764312.8397
9891.168312.99939901.571312.60029911.975310.28169917.592308.25789932.782302.0435
9943.186297.4288 9953.59292.32659963.994289.37639974.396288.29999984.573284.7271
 9994.75 279.81910004.92280.677510015.11283.9882 10025.3284.3245 10035.5286.0808
10045.69292.001610050.05294.285810066.07302.168310076.27303.681410086.46304.1363
10101.75304.043610117.04 304.35610127.23304.989310137.42306.633910147.79 308.518
#Mann= 3 , 0 , 0
9848.606    0.04       09848.606    0.04       010147.79    0.04       0
#XS Ineff= 2 , 0
       0                               0
Bank Sta=9848.606,10147.79
Exp/Cntr=0.3,0.1

Type RM Length L Ch R = 1 ,  6749.2,98.663300,98.663300,98.663300
XS GIS Cut Line= 6
818506.829906198 784818.91002874818598.605452933 784857.56778362
818655.831511513784897.283637635818678.382094445 784909.51382514
818717.728339888784924.969112186818777.030535871784942.096106215
#Sta/Elev= 30
9850.438323.91549859.195323.75069867.357320.48219869.913319.73819880.632318.6887
 9891.35318.3259 9895.14317.75059902.068314.8579    9904313.51549920.194304.3088
9924.058 301.877 9935.08294.08559943.971288.78159946.103287.67499950.077286.4481
9957.519284.54649983.749  281.339993.433279.48419999.824278.881510018.83282.2372
10030.31287.627410041.69294.064510052.65299.356310060.54301.044610063.39301.6082
10074.13302.339210084.88302.625710095.38303.523910137.01309.280410149.53310.0015
#Mann= 3 , 0 , 0
9850.438    0.06       09850.438    0.06       010149.53    0.06       0
#XS Ineff= 2 , 0
       0                               0
Bank Sta=9850.438,10149.53
Exp/Cntr=0.3,0.1

Type RM Length L Ch R = 1 ,6650.537,98.663400,98.663400,98.663400
XS GIS Cut Line= 6
818462.301125271784936.049348782818520.977258923784955.256911485
818557.450822656784965.297028982818605.580076271784974.604502818
818655.856659958784983.342554123 818752.92408477785005.551571154
#Sta/Elev= 30
9850.409315.36179863.771315.69449874.293315.54119879.179 315.6689884.815315.5572
9895.337  309.779905.859302.55169911.323299.64719916.321297.17889926.693294.3247
9937.065291.90849947.437288.08039957.668283.34569967.853281.26989978.039281.6513
9988.224280.40039998.409277.908510018.71279.536210028.86279.617210039.01278.7622
10049.16 280.47810059.41285.246410069.67290.662510079.93295.205210090.19298.6447
10100.44301.7337 10110.7302.774710120.96303.640310147.13306.743510149.61306.9601
#Mann= 3 , 0 , 0
9850.409  0.0489       09850.409  0.0489       010149.61  0.0489       0
#XS Ineff= 2 , 0
       0                               0
Bank Sta=9850.409,10149.61
Exp/Cntr=0.3,0.1

Type RM Length L Ch R = 1 ,6551.873,98.663300,98.663300,98.663300
XS GIS Cut Line= 6
818445.243625207785012.896047133818542.677850726785049.323785712
818600.940328734785079.082430916 818624.63397169785088.941847144
818665.105881677785101.156473284818725.541164821785113.734602479
#Sta/Elev= 30
9850.409 313.2839856.417  312.889860.825312.31379871.501309.43829882.177306.2025
9884.972304.02659892.853 298.1789903.529291.40519914.205288.30239924.881286.2658
9935.557285.40489942.083285.19759946.233284.93219956.983281.34819967.978279.0902
9978.972277.53449990.307 278.20610001.78277.1267 10019.9277.7124 10024.3 278.169
 10035.3283.423410045.56289.918510056.39296.926710066.53299.102910077.28299.2824
10097.94300.676510108.16301.279610118.37301.3146 10138.8301.023910149.57301.1322
#Mann= 3 , 0 , 0
9850.409  0.0488       09850.409  0.0488       010149.57  0.0488       0
#XS Ineff= 2 , 0
       0                               0
Bank Sta=9850.409,10149.57
Exp/Cntr=0.3,0.1

Type RM Length L Ch R = 1 , 6453.21,98.663400,98.663400,98.663400
XS GIS Cut Line= 6
818391.566907148785129.335427512 818446.36815795785143.199569511
818498.550106197785152.561643728818537.378169719785156.635780063
818539.378081007785156.616942809818687.287470813785170.958903179
#Sta/Elev= 30
9850.416305.84089853.957305.69289864.272 304.6289874.587304.18959884.902302.3406
9895.217301.20139905.532299.54919915.713296.32919925.873292.00449936.033289.2218
9946.192288.76519956.352287.34429966.444285.53099976.499281.39529986.554 280.003
9996.609274.840110006.65275.3802 10016.7276.258610026.74277.321610036.79276.1802
10046.84279.514810056.88286.030410066.93 292.29110076.98296.798510087.02297.4902
10097.07296.290910117.16 296.11210127.21296.599710137.26296.9834 10149.6297.7651
#Mann= 3 , 0 , 0
9850.416    0.04       09850.416    0.04       0 10149.6    0.04       0
#XS Ineff= 2 , 0
       0                               0
Bank Sta=9850.416,10149.6
Exp/Cntr=0.3,0.1

Type RM Length L Ch R = 1 ,6354.547,22.935300,22.935300,22.935300
XS GIS Cut Line= 6
818415.939088792785236.176315025818451.587206541785243.611399184
 818485.29418534785247.844658456818563.430201748785250.831127636
818648.407774724785254.612494631818713.729763736785259.484744665
#Sta/Elev= 29
 9850.42302.65419859.676 299.3829869.891295.25319880.106293.58349890.275 291.386
9900.353289.84439910.432 288.423 9920.51287.9919 9930.52285.97489940.527284.7603
9950.534283.87599960.542283.34229970.549282.36289980.556280.99969990.564276.1393
10000.61273.508310010.63 275.39210020.64280.532710030.64286.271510040.65 290.258
10050.66292.140910060.67290.613110070.68290.615610080.68290.446410110.76290.5015
10120.79290.983710130.82294.937610140.84 298.118 10149.6298.8684
#Mann= 3 , 0 , 0
 9850.42    0.04       0 9850.42    0.04       0 10149.6    0.04       0
#XS Ineff= 2 , 0
       0                               0
Bank Sta=9850.42,10149.6
Exp/Cntr=0.3,0.1

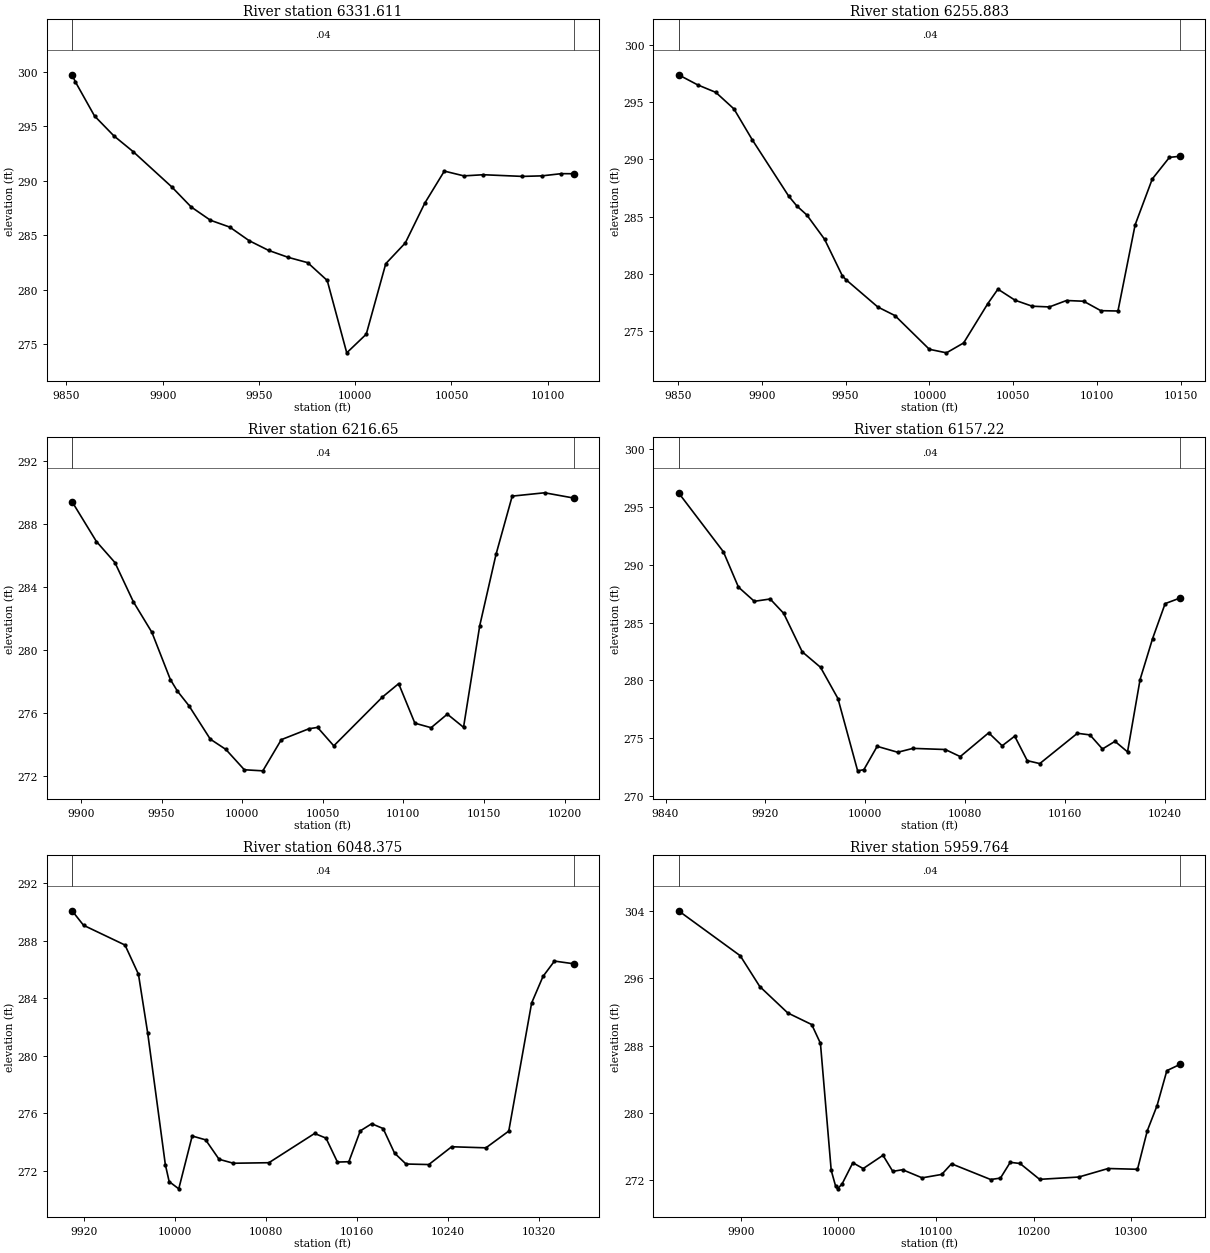
Type RM Length L Ch R = 1 ,6331.611,75.728000,75.728000,75.728000
XS GIS Cut Line= 3
818413.375455618785256.152990952818501.584772319785263.740889162
818671.363994837785292.195507467
#Sta/Elev= 26
9852.937299.74399854.567299.12539864.604295.95899874.641294.13469884.678292.6822
9904.752289.43799914.789287.60219924.826286.37749934.863285.74829944.935   284.5
9955.074283.60539965.214282.96969975.353282.48079985.493280.84379995.632274.1954
10005.77275.908810015.91282.387810026.05284.291810036.19287.953210046.33290.8939
10056.47290.454710066.61290.560410086.89290.406910097.03290.456210107.17290.6596
10113.62290.6503
#Mann= 3 , 0 , 0
9852.937    0.04       09852.937    0.04       010113.62    0.04       0
#XS Ineff= 2 , 0
       0                               0
Bank Sta=9852.937,10113.62
Exp/Cntr=0.3,0.1

Type RM Length L Ch R = 1 ,6255.883,39.233800,39.233800,39.233800
XS GIS Cut Line= 6
818404.532613501785297.600010753818475.314248789785327.447205069
818514.361733767785340.993042791818544.069917212785347.595725468
818546.039978147785347.940486132818691.361965886785378.944385145
#Sta/Elev= 29
9850.419297.36729861.779296.48999872.632 295.8339883.485294.38469894.337291.7031
9916.043286.78969920.938285.92219926.896285.13539937.489283.01419948.073279.8258
9950.281279.48299969.221277.10389979.465276.35249999.944273.412610010.16273.1028
10020.39273.966510034.83277.402610040.84278.660210051.06277.693810061.29277.1712
10071.51 277.10910081.74277.669910091.96277.605910102.19276.782210112.41276.7531
10122.64284.270610132.86288.273810143.09290.158210149.59290.2607
#Mann= 3 , 0 , 0
9850.419    0.04       09850.419    0.04       010149.59    0.04       0
#XS Ineff= 2 , 0
       0                10035.76       0
Bank Sta=9850.419,10149.59
Exp/Cntr=0.3,0.1

Type RM Length L Ch R = 1 , 6216.65,59.429500,59.429500,59.429500
XS GIS Cut Line= 3
818441.830073923785332.980460376818571.772830784785406.013980672
818733.015667856785424.035238937
#Sta/Elev= 27
9894.473289.4108 9909.58286.88439921.051285.55129932.523283.05669943.994281.1238
9955.465278.12589959.824277.39539966.936276.47449980.234274.34589989.879 273.695
10001.35272.404110012.82272.336210024.29274.314510041.46 275.00710046.78275.0917
10056.84273.921710087.03277.018910097.09277.866610107.15275.359110117.22275.0729
10127.28 275.93310137.34275.0985 10147.4281.552710157.47286.061610167.53289.7643
10187.65289.976210205.78289.6403
#Mann= 3 , 0 , 0
9894.473    0.04       09894.473    0.04       010205.78    0.04       0
#XS Ineff= 2 , 0
       0                10023.37       0
Bank Sta=9894.473,10205.78
Exp/Cntr=0.3,0.1

Type RM Length L Ch R = 1 , 6157.22,108.845000,108.845000,108.845000
XS GIS Cut Line= 6
818384.748469025  785336.4570546818457.425846845785388.082989186
818515.744298995785451.738203764818541.664802819785473.949837133
818581.192567319785496.895100489818727.116076976785482.488612816
#Sta/Elev= 30
9850.447296.25129886.398291.14279898.469288.08249911.183286.85319923.897 287.053
9934.702285.81439949.598282.47889964.252281.1392 9978.23278.43129994.012272.1714
    9999272.272610009.66274.293110026.14  273.7810038.33274.116610064.27274.0183
10076.26273.405110099.05275.463610109.86274.340510119.91275.173710129.96273.0536
10140.01 272.79910170.16275.423610180.21275.283810190.25274.0644 10200.3274.7265
10210.35273.8136 10220.4280.073210230.45283.6287 10240.5 286.65310252.67287.1459
#Mann= 3 , 0 , 0
9850.447    0.04       09850.447    0.04       010252.67    0.04       0
#XS Ineff= 2 , 0
       0                10020.51       0
Bank Sta=9850.447,10252.67
Exp/Cntr=0.3,0.1

Type RM Length L Ch R = 1 ,6048.375,88.611300,88.611300,88.611300
XS GIS Cut Line= 3
818335.599498928785449.644395381818465.542255849785531.214301184
818751.985413373785506.553632006
#Sta/Elev= 30
9909.684290.07439919.757289.06669956.204287.69179968.011285.66489976.184281.5488
9991.625272.43519994.992271.248510003.43270.743810015.24 274.41810027.05274.1483
10038.85272.799110051.42272.522710082.64272.560310122.79274.593510132.82  274.27
10142.86272.6049 10152.9272.629210162.93274.773310172.97275.270110183.01274.9368
10193.04273.228310203.08272.470210223.15272.432110243.23273.669710273.34273.5944
10293.41274.758610313.49283.661210323.52285.513310333.56286.577210350.61286.3885
#Mann= 3 , 0 , 0
9909.684    0.04       09909.684    0.04       010350.61    0.04       0
#XS Ineff= 2 , 0
       0                10028.16       0
Bank Sta=9909.684,10350.61
Exp/Cntr=0.3,0.1

Type RM Length L Ch R = 1 ,5959.764,48.983800,48.983800,48.983800
XS GIS Cut Line= 6
818231.857871443785588.706072569818309.914374679 785590.59227933
818366.922713369785578.587062716818409.631732732 785558.36658445
818428.913083345785554.423256233818738.748324931785528.186729789
#Sta/Elev= 30
 9836.01304.06029899.246298.70389919.303 295.0319947.991291.88289972.563290.4983
9981.484288.2651 9992.53273.11889997.055271.23929999.055270.918110003.65271.4936
 10014.7274.0265 10025.3273.332910045.61 274.91710055.65273.000510065.68273.1968
10085.75272.228710105.83272.635510115.86273.9045   10156272.028910166.04272.2003
10176.08274.077210186.11273.939810206.18272.050510246.33272.324710276.43273.3413
10306.54273.248910316.58277.841410326.61280.841310336.65285.006510350.45285.7687
#Mann= 3 , 0 , 0
 9836.01    0.04       0 9836.01    0.04       010350.45    0.04       0
#XS Ineff= 2 , 0
       0                10016.77       0
Bank Sta=9836.01,10350.45
Exp/Cntr=0.3,0.1

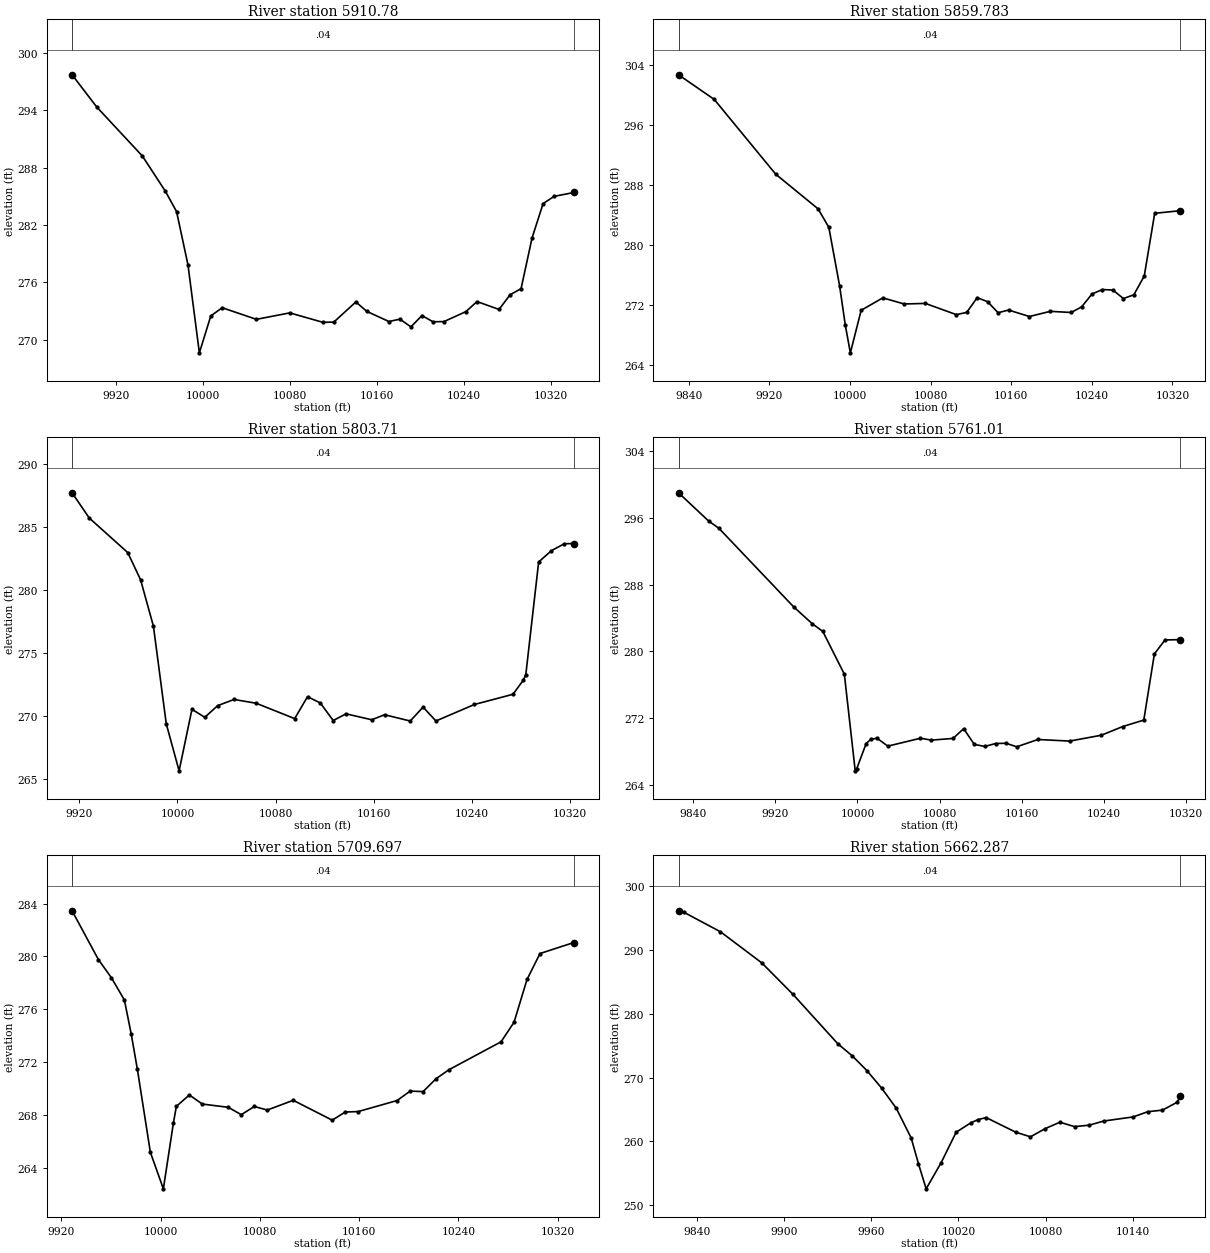
Type RM Length L Ch R = 1 , 5910.78,50.997500,50.997500,50.997500
XS GIS Cut Line= 3
818303.350931495785644.084287092818474.078641295785590.020512342
818752.933900625 785544.49312304
#Sta/Elev= 30
9879.552297.73679902.261294.36129944.219289.23359965.197285.58229975.687283.4165
9986.176277.84039996.666268.628110007.16272.488110017.64273.352110049.11272.1354
10079.83272.811610110.23271.824410120.36271.845610140.63273.954610150.76272.9638
10171.03271.907510181.16272.152510191.29271.346610201.42272.531710211.56  271.88
10221.69271.900210241.95272.947810252.08273.996110272.35273.171410282.48274.7025
10292.61275.344210302.75280.666810312.88284.249310323.01285.008210341.18285.4135
#Mann= 3 , 0 , 0
9879.552    0.04       09879.552    0.04       010341.18    0.04       0
#XS Ineff= 2 , 0
       0                10013.67       0
Bank Sta=9879.552,10341.18
Exp/Cntr=0.3,0.1

Type RM Length L Ch R = 1 ,5859.783,56.073000,56.073000,56.073000
XS GIS Cut Line= 6
818269.574468791 785691.44160302818310.774587542785690.219518691
818355.924578011  785682.7353829818392.357266456785671.933246017
818506.347976208785630.015709966818749.549698025785565.576098233
#Sta/Elev= 30
9829.729  302.699865.171299.4023 9926.18 289.4299968.225284.80739978.912282.3432
9989.598274.54629995.238269.316810000.29265.595710011.03271.274610032.51272.9289
10053.74272.115210074.78272.186610105.57270.688910115.85 270.99710126.21 272.962
10136.58272.410310146.94270.9451 10157.3 271.30710178.03270.442310198.76271.1324
10219.48270.979210229.84271.728410240.21273.452310250.57274.042410260.93273.9704
 10271.3272.836710281.66273.335410292.02275.833210302.39284.209310327.83284.5592
#Mann= 3 , 0 , 0
9829.729    0.04       09829.729    0.04       010327.83    0.04       0
#XS Ineff= 2 , 0
       0                 10022.5       0
Bank Sta=9829.729,10327.83
Exp/Cntr=0.3,0.1

Type RM Length L Ch R = 1 , 5803.71,42.700000,42.700000,42.700000
XS GIS Cut Line= 2
818371.642015457785734.190578371818762.418773443785612.784206972
#Sta/Elev= 30
9914.059287.75219928.047285.75159959.462283.00569969.933280.84549980.405277.1605
9990.876269.409810001.35265.682110011.82270.568510022.29269.929510032.76270.8565
10046.15271.346710064.18271.047310095.59269.827310106.06271.568310116.53271.0647
10127.01269.676110137.48270.206710158.42269.735710168.89270.135610189.83269.6364
10200.31  270.7410210.78269.639510242.19270.949410273.61271.758410282.09272.8847
10284.08 273.32110294.55282.259310305.02283.162310315.49 283.70810323.26283.7192
#Mann= 3 , 0 , 0
9914.059    0.04       09914.059    0.04       010323.26    0.04       0
#XS Ineff= 2 , 0
       0                   10025       0
Bank Sta=9914.059,10323.26
Exp/Cntr=0.3,0.1

Type RM Length L Ch R = 1 , 5761.01,51.312200,51.312200,51.312200
XS GIS Cut Line= 6
818296.036371827785765.970869452818351.649226516 785772.19908075
818407.604978234785767.357299849818444.741029471785757.139854848
818554.066967726785718.659536853818769.490694523785662.788456187
#Sta/Elev= 30
9825.524 298.9759854.793295.60439864.836294.73319937.788285.32369955.829283.3157
9966.201282.3847 9987.18277.27279997.786265.70719999.099265.912610008.39268.9494
10012.79269.466310018.99269.614310029.59268.661910061.39 269.60710071.99269.3817
10093.17269.584110103.52270.750810113.87268.871610124.22268.623910134.57268.9774
 10144.9269.006210155.22268.581310175.88269.457110206.85269.267210237.83269.9703
10258.49271.001910279.14 271.77910289.47279.695210299.79281.365110314.76281.4055
#Mann= 3 , 0 , 0
9825.524    0.04       09825.524    0.04       010314.76    0.04       0
#XS Ineff= 2 , 0
       0                10025.34       0
Bank Sta=9825.524,10314.76
Exp/Cntr=0.3,0.1

Type RM Length L Ch R = 1 ,5709.697,47.410700,47.410700,47.410700
XS GIS Cut Line= 2
818414.707131743785818.992928803818801.063939005785700.177824631
#Sta/Elev= 30
9928.756283.45229949.987 279.7599960.449278.38669970.911276.7023 9976.36274.1502
9981.373271.45599991.836265.1802 10002.3262.419110010.38267.393110012.76268.6555
10023.22269.520710033.68268.831910054.61268.586310065.07 268.02710075.53268.6484
   10086268.379510106.92269.116410138.31267.613310148.77268.227610159.23268.2639
10190.62269.100710201.08269.812610211.54269.7754   10222270.751210232.47271.4356
10274.31273.541310284.78275.018110295.24278.2573 10305.7280.218710332.97281.0512
#Mann= 3 , 0 , 0
9928.756    0.04       09928.756    0.04       010332.97    0.04       0
#XS Ineff= 2 , 0
       0                10026.12       0
Bank Sta=9928.756,10332.97
Exp/Cntr=0.3,0.1

Type RM Length L Ch R = 1 ,5662.287,46.962000,46.962000,46.962000
XS GIS Cut Line= 6
 818331.30349373785814.918983168818410.702113997785844.523083644
818452.356622178785850.897549339818475.966865494785848.332699693
818568.052168596785827.469197746818667.192271317785814.709539829
#Sta/Elev= 30
9827.462296.12679831.407295.86069856.318292.8365 9884.77287.95899906.115283.0529
9937.052275.2901 9947.08273.37819957.117271.07239967.175268.34589977.234265.1973
9987.498260.53239992.444256.54219997.784252.573610008.09256.666710018.41261.4371
10028.72262.944510033.56263.418610039.01263.736510059.37261.449110069.55260.7213
10079.66262.004410089.75263.007210099.83262.316810109.91262.544810119.99263.1962
10140.16263.835910150.24264.653810160.32264.904810170.41266.133410172.62267.0825
#Mann= 3 , 0 , 0
9827.462    0.04       09827.462    0.04       010172.62    0.04       0
#XS Ineff= 2 , 0
       0                10025.75       0
Bank Sta=9827.462,10172.62
Exp/Cntr=0.3,0.1

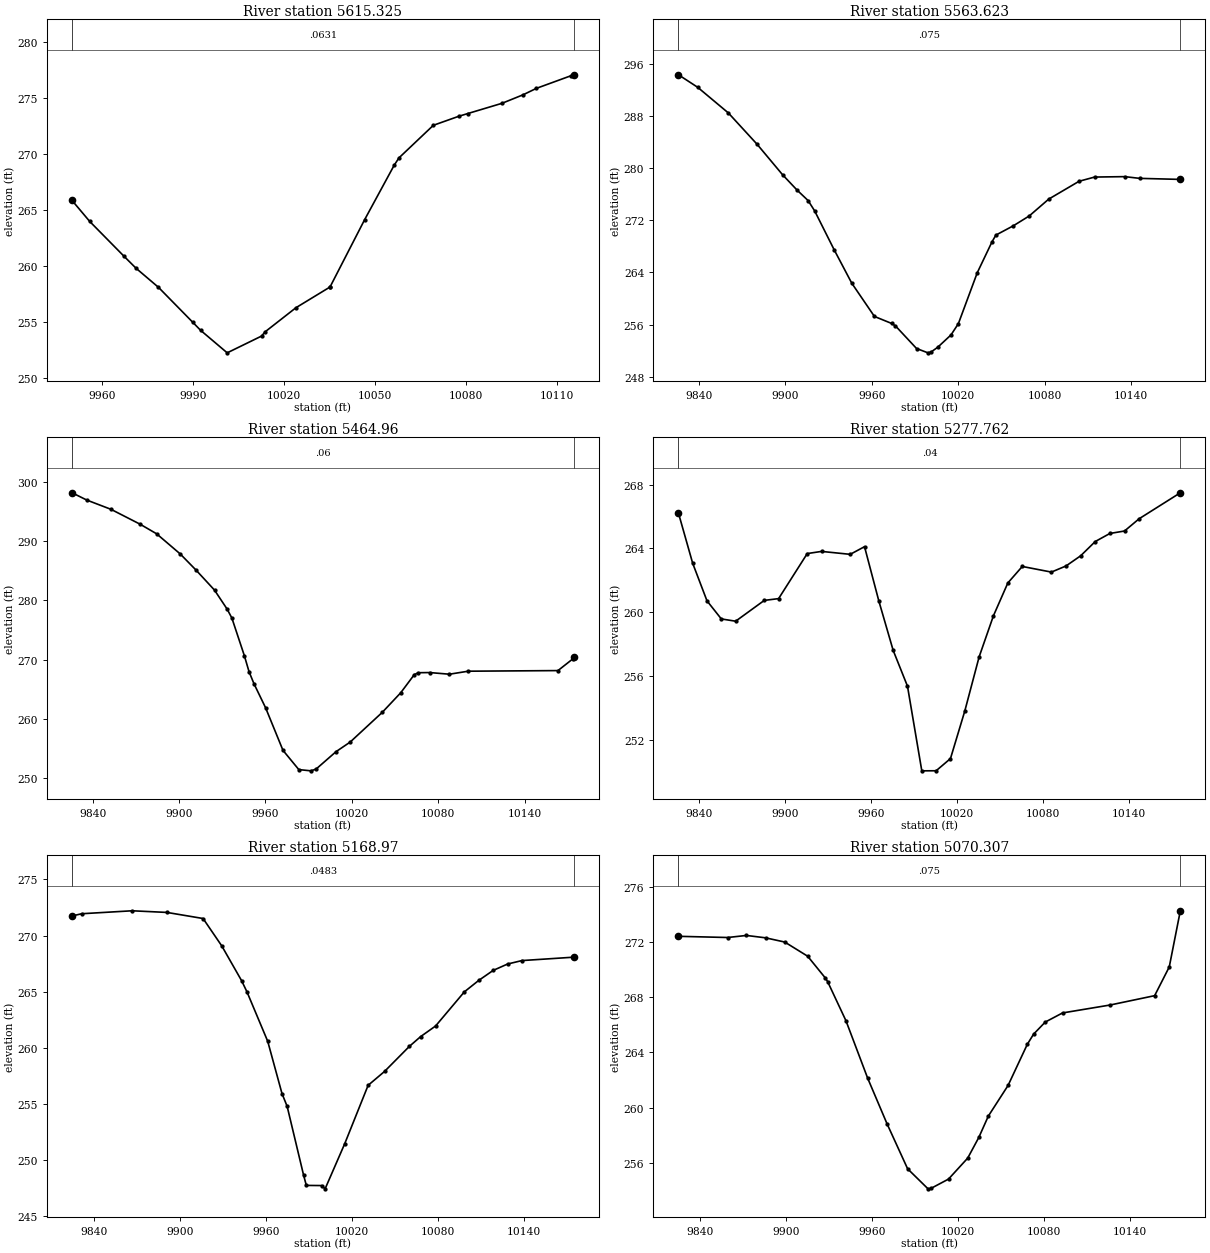
Type RM Length L Ch R = 1 ,5615.325,51.701300,51.701300,51.701300
XS GIS Cut Line= 2
818459.851332158785865.081822544 818605.91837275785942.857779235
#Sta/Elev= 24
9950.025265.86959955.858263.99179967.187260.87399971.128259.80869978.517258.1041
9989.846254.97339992.405254.261210001.18252.2465 10012.5253.745110013.68254.1258
10023.83256.277610034.96258.113410035.16258.174110046.49264.150210056.24269.0218
10057.82269.680410069.15272.592110077.51273.396910080.48273.640610091.81274.5616
10098.79275.326110103.14 275.89710114.47277.018310115.51277.1105
#Mann= 3 , 0 , 0
9950.025  0.0631       09950.025  0.0631       010115.51  0.0631       0
#XS Ineff= 2 , 0
       0                10016.06       0
Bank Sta=9950.025,10115.51
Exp/Cntr=0.3,0.1

Type RM Length L Ch R = 1 ,5563.623,98.663400,98.663400,98.663400
XS GIS Cut Line= 6
818344.245369726785828.732520024818424.808624497785877.412896115
818494.440721581785948.168512946818533.992737915785978.490716875
818581.783167951786000.436283415818632.899233996786010.863875355
#Sta/Elev= 30
9825.782294.29319839.119292.37469860.398288.44799880.352283.64869898.067278.9722
9908.172276.61279915.781275.01969920.314273.44499933.865267.48079946.116262.3524
9961.834 257.2629973.821256.18599976.455255.80969991.075252.3505    9999251.6861
 10001.1251.8049 10005.8252.547110014.99254.428910020.13256.165910033.24263.9666
10043.41268.669510046.14 269.72710058.33271.161110069.29272.657510082.85275.2425
10103.92277.975810114.68278.620610135.63278.685610145.96278.420510174.21278.2612
#Mann= 3 , 0 , 0
9825.782   0.075       09825.782   0.075       010174.21   0.075       0
#XS Ineff= 2 , 0
       0                               0
Bank Sta=9825.782,10174.21
Exp/Cntr=0.3,0.1

Type RM Length L Ch R = 1 , 5464.96,187.198000,187.198000,187.198000
XS GIS Cut Line= 6
818276.341401386785830.293357721818315.066978291785857.206149938
818347.793056348785891.535604948818438.122947006786042.119214599
818462.647016832786061.930463885818505.689293234786077.923491445
#Sta/Elev= 30
9825.755298.16159835.992296.93049852.752 295.3739872.874292.87639884.431291.2473
9900.831287.84659911.847285.11449924.637281.7488 9933.39278.54479936.683277.0414
9945.355270.69089948.583268.00779952.052265.94959960.108261.89919972.167254.7259
9983.158251.47999991.584251.26989995.153251.568110008.97254.499210018.79 256.117
10041.07261.126810053.87264.424810063.35267.502410066.24267.817410074.02267.8441
 10087.7267.564510100.77268.072810163.07268.176110173.43270.158610174.14270.4043
#Mann= 3 , 0 , 0
9825.755    0.06       09825.755    0.06       010174.14    0.06       0
#XS Ineff= 2 , 0
       0                               0
Bank Sta=9825.755,10174.14
Exp/Cntr=0.3,0.1

Type RM Length L Ch R = 1 ,5277.762,108.792000,108.792000,108.792000
XS GIS Cut Line= 6
818065.081107108786050.941537333818239.332740919786047.400247526
818241.330839389786047.487439879818290.296824347786045.421169107
818312.832562716786048.424307521818413.149453193786069.359736721
#Sta/Elev= 30
9825.341266.20549835.262263.06179845.264 260.7039855.266259.56969865.268259.4274
9885.272260.73239895.274260.84449915.278263.6697 9925.28 263.8059945.285263.6215
9955.287 264.1029965.289260.69369975.291257.59819985.293255.34939995.295250.0418
 10005.3250.046710015.31250.810110025.32253.795610035.33257.190910045.34259.7722
10055.38261.825910065.47262.8614 10085.8262.507910096.02262.892310106.23263.5301
10116.45264.426310126.66264.930910136.88265.0852 10147.1265.854910175.85267.4828
#Mann= 3 , 0 , 0
9825.341    0.04       09825.341    0.04       010175.85    0.04       0
#XS Ineff= 2 , 0
       09932.034                       0
Bank Sta=9825.341,10175.85
Exp/Cntr=0.3,0.1

Type RM Length L Ch R = 1 , 5168.97,98.663300,98.663300,98.663300
XS GIS Cut Line= 6
818169.231060221786236.484811929818251.670589577786180.332397271
818327.005602112786100.529508425818347.495441756786084.961761539
818382.795668535786078.736393977818461.047640528786087.260758411
#Sta/Elev= 27
9824.772271.74199831.538271.93999866.726272.2028    9891 272.0569916.239271.5145
9929.257269.08279943.074265.99539946.877264.98889961.369260.58759971.328 255.941
9974.934 254.7979986.366248.70099988.324247.7635    9999247.750210001.43247.4587
10015.09251.462110031.47256.671510042.91257.9031 10060.3260.140310068.13261.0058
10078.57  261.9510098.65264.987410108.71266.008310118.77266.896610128.83267.4648
10138.88267.771910175.15268.0748
#Mann= 3 , 0 , 0
9824.772  0.0483       09824.772  0.0483       010175.15  0.0483       0
#XS Ineff= 2 , 0
       0                               0
Bank Sta=9824.772,10175.15
Exp/Cntr=0.3,0.1

Type RM Length L Ch R = 1 ,5070.307,134.497800,134.497800,134.497800
XS GIS Cut Line= 6
 818247.94941683786313.714763847818307.616218965786263.957608252
818399.815219088 786169.45242888818428.288544199786143.868319237
818465.912567175 786121.63051046818522.568879892786106.930020727
#Sta/Elev= 27
9824.732272.41179859.046272.32569872.196272.47489885.579272.30229898.961271.9958
9914.968270.96849927.374269.3803 9928.93269.12159941.705 266.2919956.852262.1306
9970.365258.82769984.774255.55759999.026254.1062   10001254.133510013.32254.8127
10026.73256.333910034.49257.832610041.15259.382510054.91261.600110068.35264.5812
10072.77265.324410080.88266.195410092.96266.857510126.17267.431810157.28268.1094
10167.49270.190710175.22274.2631
#Mann= 3 , 0 , 0
9824.732   0.075       09824.732   0.075       010175.22   0.075       0
#XS Ineff= 2 , 0
       0                               0
Bank Sta=9824.732,10175.22
Exp/Cntr=0.3,0.1

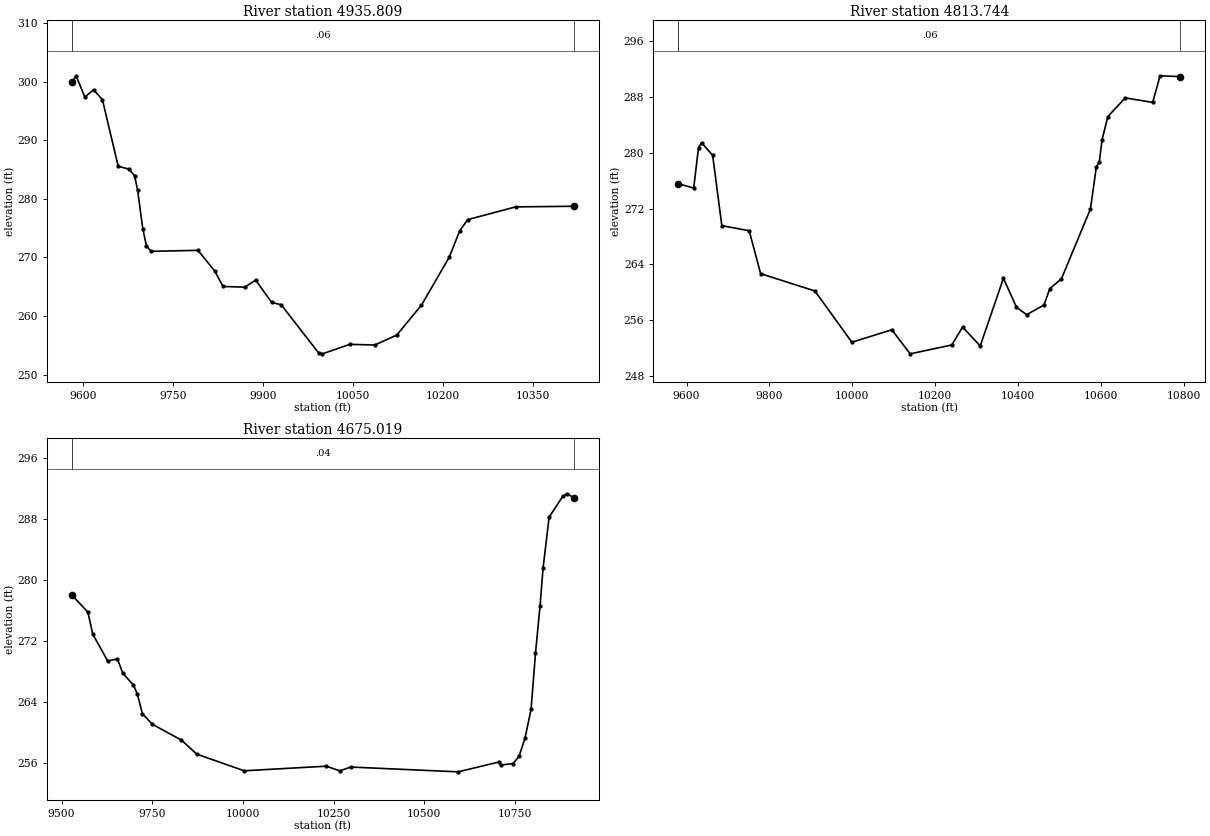
Type RM Length L Ch R = 1 ,4935.809,122.064600,122.064600,122.064600
XS GIS Cut Line= 6
 818188.73227729786579.533932946818312.745318125786463.838466551
818388.139854085786386.613878976818437.220332246786330.385719385
818608.897329971786124.906717358818751.973214988785961.810201828
#Sta/Elev= 30
9581.569299.89189588.216301.02599602.875297.38749617.493298.64849632.194296.9303
9658.521285.55539676.171285.10069685.874283.94579690.831281.4756 9699.55274.8757
 9705.49271.98039713.226271.03779791.474271.21369819.425267.69099833.401265.0383
9869.529264.92519887.786266.12559914.334262.31969930.356261.91899992.692253.6854
    9999253.534210044.86255.160310086.38255.041310123.12256.742310164.27 261.862
10210.75 270.08110227.97274.535810241.27276.454110321.09278.630910418.45 278.742
#Mann= 3 , 0 , 0
9581.569    0.06       09581.569    0.06       010418.45    0.06       0
#XS Ineff= 2 , 0
       0                10096.43       0
Bank Sta=9581.569,10418.45
Exp/Cntr=0.3,0.1

Type RM Length L Ch R = 1 ,4813.744,138.725400,138.725400,138.725400
XS GIS Cut Line= 6
818223.629203051786584.692385033 818300.49791497786540.584682375
818431.145693302786480.861142144 818511.81258446786423.390089005
818701.245562971786216.835576922819121.705888122785790.080722094
#Sta/Elev= 30
9580.493275.54259617.233274.95429628.944280.7464 9636.18281.43729662.984279.6523
9685.115269.54269751.087268.81019778.813262.64529909.684260.1595    9999252.7957
10095.28  254.5910139.61251.132710239.97252.406110266.17254.977310308.68252.2677
10364.68261.9867 10396.2257.826510420.68256.747110462.68258.152410476.68260.5005
10504.69261.909410574.69 271.93810588.69277.902310596.24278.745110602.69281.8674
10616.69285.206910658.69287.886210724.84287.238910742.69291.059610791.57290.9424
#Mann= 3 , 0 , 0
9580.493    0.06       09580.493    0.06       010791.57    0.06       0
#XS Ineff= 2 , 0
       0                10105.38       0
Bank Sta=9580.493,10791.57
Exp/Cntr=0.3,0.1

Type RM Length L Ch R = 1 ,4675.019,0.000000,0.000000,0.000000
XS GIS Cut Line= 4
818323.094777048786770.115444362818616.497554839 786497.54599987
818751.914221495786393.379333198819399.483665973  785903.7959999
#Sta/Elev= 30
9529.006277.99079572.554275.77749586.204272.88199627.152269.39219654.062 269.653
9668.755267.7756 9698.14266.24269709.047265.04389722.697262.48859749.995261.1106
9830.373259.02729872.839 257.18710003.29255.011410229.56255.614210267.17254.9991
10296.62255.503210593.11 254.87310705.94256.166910711.16255.763410744.32255.9608
10760.91256.888910777.49259.319610794.07263.076110806.23270.424310818.76276.5907
10827.23281.608410843.81288.216810881.44 290.94610893.98291.278410912.14290.7294
#Mann= 3 , 0 , 0
9529.006    0.04       09529.006    0.04       010912.14    0.04       0
#XS Ineff= 2 , 0
       0                10125.91       0
Bank Sta=9529.006,10912.14
Exp/Cntr=0.3,0.1